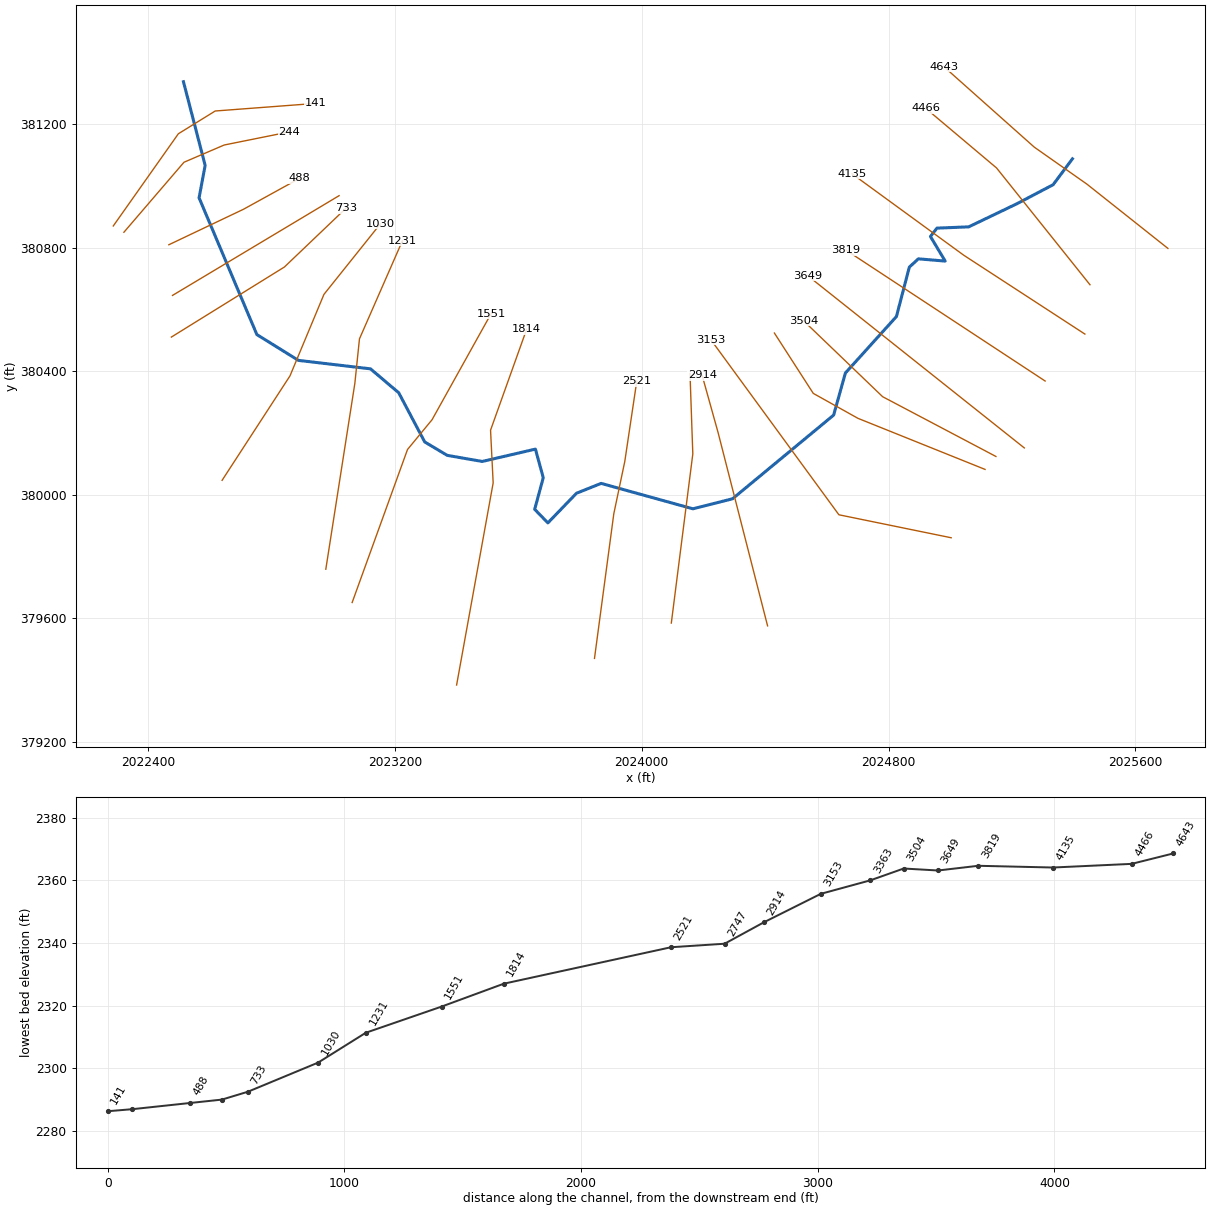
--- TOMSCK.prj (project) ---

Proj Title=TOMSCK
Current Plan=p01
Default Exp/Contr=0,0
English Units
Geom File=g01
Flow File=f01
Plan File=p01
BEGIN DESCRIPTION:
Stream Name- Toms Creek
Flood Zone: Zone A
Greenbrier County, WV
County-Wide Study
WVDHSEM-2018-3, Flood Risk Project
HEC-RAS Version: 5.0.7
General Notes:
For the Hydrology Regression was used.
END DESCRIPTION:
DSS File=dss
DSS Export Rating Curves= 0
DSS Export Rating Curve Sorted= 0
DSS Export Volume Flow Curves= 0
DXF OffsetX= 0
DXF OffsetY= 0
DXF ScaleX= 0
DXF ScaleY= 0

--- TOMSCK.p01 (plan) ---

Plan Title=Floodplain
Program Version=5.07
Short Identifier=Floodplain
Geom File=g01
Flow File=f01
Subcritical Flow
K Sum by GR= 0
Std Step Tol= 0.01
Critical Tol= 0.01
Num of Std Step Trials= 20
Max Error Tol= 0.3
Flow Tol Ratio= 0.001
Split Flow NTrial= 30
Split Flow Tol= 0.02
Split Flow Ratio= 0.02
Log Output Level= 0
Friction Slope Method= 1
Unsteady Friction Slope Method= 2
Unsteady Bridges Friction Slope Method= 1
Parabolic Critical Depth
Global Vel Dist= 0 , 0 , 0
Global Log Level= 0
CheckData=True
Encroach Param=-1 ,0,0, 0
Mapping Interval=1HOUR
Computation Time Step Use Courant=        0
Computation Time Step Use Time Series=    0
Computation Time Step Count To Double=0
Computation Time Step Max Doubling=0
Computation Time Step Max Halving=0
Computation Time Step Residence Courant=0
Run HTab= 0
Run UNet= 0
Run Sediment= 0
Run PostProcess= 0
Run WQNet= 0
Run RASMapper= 0
UNET Theta= 0
UNET Theta Warmup= 0
UNET ZTol= 0
UNET ZSATol= 0
UNET MxIter= 0
UNET Max Iter WO Improvement= 0
UNET MaxInSteps= 0
UNET DtIC= 0
UNET DtMin= 0
UNET MaxCRTS= 0
UNET WFStab= 0
UNET SFStab= 0
UNET WFX= 1
UNET SFX= 1
UNET 1D Methodology=Finite Difference
UNET DSS MLevel= 1
UNET Pardiso=0
UNET DZMax Abort= 0
UNET Use Existing IB Tables= 0
UNET Froude Reduction=False
UNET Froude Limit= 0
UNET Froude Power= 0
UNET D1 Cores= 0
UNET D2 Coriolis=0
UNET D2 Cores= 0
UNET D2 Theta= 1
UNET D2 Theta Warmup= 1
UNET D2 Z Tol= 0.01
UNET D2 Volume Tol= 0.01
UNET D2 Max Iterations= 20
UNET D2 Equation= 0
UNET D2 RampUpFraction=0.1
UNET D2 TimeSlices= 1
UNET D2 BCVolumeCheck=0
UNET D1D2 MaxIter= 0
UNET D1D2 ZTol=0.01
UNET D1D2 QTol=0.1
UNET D1D2 MinQTol=1
DSS File=dss
Write IC File= 0
Write IC File at Fixed DateTime=0
Write IC File at Sim End=0
Echo Input=False
Echo Parameters=False
Echo Output=False
Write Detailed= 0
HDF Write Warmup=0
HDF Write Time Slices=0
HDF Flush=0
HDF Face Node Velocities=0
HDF Compression= 1
HDF Chunk Size= 1
HDF Spatial Parts= 1
HDF Use Max Rows=0
HDF Fixed Rows= 1
Calibration Method= 0
Calibration Iterations= 20
Calibration Max Change=0.05
Calibration Tolerance=0.2
Calibration Maximum=1.5
Calibration Minimum=0.5
Calibration Optimization Method= 1
WQ AD Non Conservative
WQ ULTIMATE=-1
WQ Max Comp Step=1HOUR
WQ Output Interval=15MIN
WQ Output Selected Increments= 0
WQ Output face flow=0
WQ Output face velocity=0
WQ Output face area=0
WQ Output face dispersion=0
WQ Output cell volume=0
WQ Output cell surface area=0
WQ Output cell continuity=0
WQ Output cumulative cell continuity=0
WQ Output face conc=0
WQ Output face dconc_dx=0
WQ Output face courant=0
WQ Output face peclet=0
WQ Output face adv mass=0
WQ Output face disp mass=0
WQ Output cell mass=0
WQ Output cell source sink temp=0
WQ Output nsm pathways=0
WQ Output nsm derived pathways=0
WQ Output MaxMinRange=-1
WQ Daily Max Min Mean=-1
WQ Daily Range=0
WQ Daily Time=0
WQ Create Restart=0
WQ Fixed Restart=0
WQ System Summary=0
WQ Write To DSS=0
WQ Use Fixed Temperature=0
Sorting and Armoring Iterations= 10
XS Update Threshold= 0.02
Bed Roughness Predictor= 0
Hydraulics Update Threshold= 0.02
Energy Slope Method= 1
Volume Change Method= 0
Sediment Retention Method= 0
XS Weighting Method= 0
Number of US Weighted Cross Sections= 1
Number of DS Weighted Cross Sections= 1
Upstream XS Weight=0.25
Main XS Weight=0.5
Downstream XS Weight=0.25
Number of DS XS's Weighted with US Boundary= 1
Upstream Boundary Weight= 1
Weight of XSs Associated with US Boundary= 0
Number of US XS's Weighted with DS Boundary= 1
Downstream Boundary Weight= 0.5
Weight of XSs Associated with DS Boundary= 0.5
Percentile Method= 0
Sediment Output Level= 4
Mass or Volume Output= 0
Output Increment Type= 1
Profile and TS Output Increment= 10
XS Output Flag= 0
XS Output Increment= 10
Write Gradation File= 0
Read Gradation Hotstart= 0
Write HDF5 File= 1
Write Binary Output= 1
Write DSS Sediment File= 0
SV Curve= 0
Specific Gage Flag= 0

--- TOMSCK.f01 (steady flow) ---

Flow Title=NFF Regression Equation
Program Version=5.07
Number of Profiles= 6
Profile Names=f1p,f10p,f4p,f2p,f02p,f1plus
River Rch & RM=TOMSCK,Main            ,4643
     535     282     376     453     748     791
River Rch & RM=TOMSCK,Main            ,3153
     635     337     447     538     886     939
Boundary for River Rch & Prof#=TOMSCK,Main            , 1
Up Type= 0
Dn Type= 3
Dn Slope=0.00747
DSS Import GetInterval= 0
DSS Import GetPeak= 0
DSS Import FillOption= 0

--- TOMSCK.g01 (geometry) ---

Geom Title=USGS 10m DEM
Program Version=5.07

River Reach=TOMSCK          ,Main
Reach XY= 30
2025395.80947734381088.523775309  2025333.102154381004.571740314
2025215.73481022 380942.865679922025059.68387692380868.067542493
2024956.66015683380863.8798771952024935.64318551380836.771417111
2024983.42926149380757.152626902 2024896.4980009380764.433675319
2024867.23105071380737.5438195022024825.43039422380577.497788608
2024659.99635883380394.2990245972024621.98843582380258.099310711
2024294.37092973379986.9431439042024165.90462179379954.463961214
2023868.58188353380036.8286958932023788.71669942 380004.88119286
2023696.07725929379908.8451834172023653.30133878379952.832749631
 2023681.1021841  380055.19169042023655.67500712380147.871355664
2023483.44817151380107.8819639092023369.86607571380127.660361812
2023296.98286353380171.1266879142023212.71040939380330.536792219
2023121.31657611380407.9549300072022887.83636732380435.395059407
2022753.08228843 380519.027331012022565.87918372380962.049543321
2022585.52145301381067.2785658992022515.23768948 381338.28594242

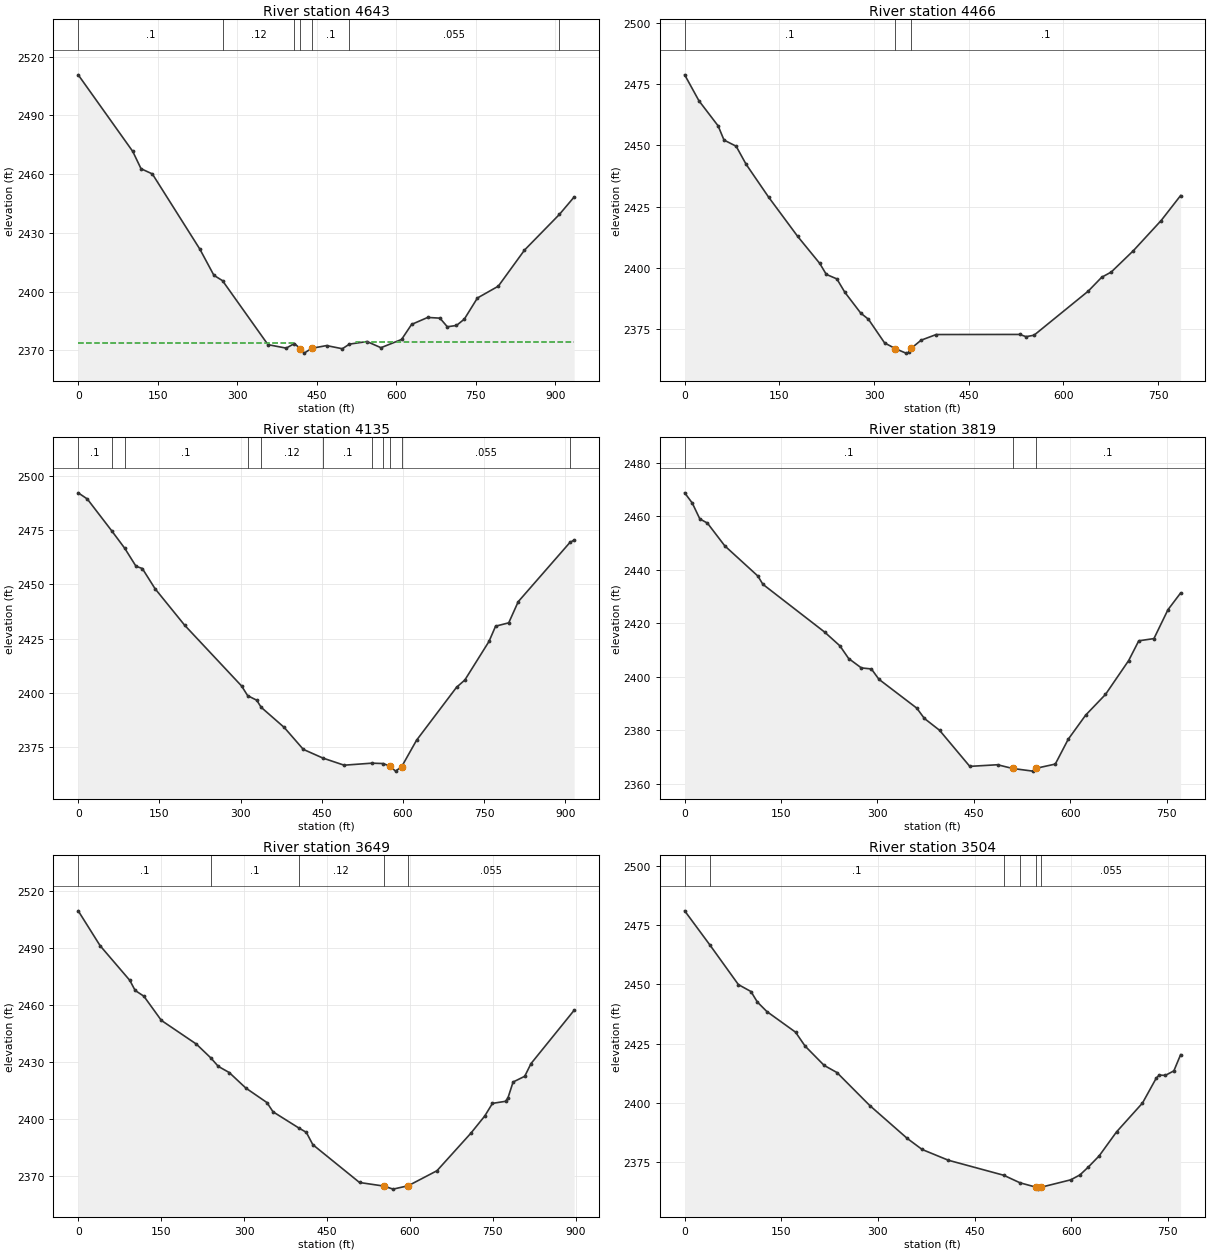
Type RM Length L Ch R = 1 ,4643    ,176.9,176.9,176.9
XS GIS Cut Line= 4
2025705.16689216380798.1689580132025442.86570535381006.317641733
 2025271.9468675381126.4685079452024979.18489772381387.077429024
#Sta/Elev= 30
       0 2510.72   102.9  2471.6   118.5 2462.78   139.9  2460.1   229.6 2421.65
     256 2408.34  272.252405.595     358 2372.92   392.4 2371.14  407.992373.492
  419.072370.834   426.5 2368.59   440.5 2371.05   468.6 2372.45   498.3 2370.83
  511.672373.185   544.9  2374.5   571.2 2371.36   610.1 2375.57     629 2383.25
   659.4 2386.82   682.5 2386.45   696.4 2382.05   713.7 2382.72   728.5 2385.96
   753.2 2396.75   792.6 2402.78     842  2421.2  907.982439.461   935.7 2448.33
#Mann= 7 ,-1 , 0
       0      .1       0  272.25     .12       0  407.99      .1       0
  419.07    .045       0   440.5      .1       0  511.67    .055       0
  907.98      .1       0
#XS Ineff= 2 , 0
          408.39 2373.96  524.28         2374.23
Permanent Ineff=
       F       F
Bank Sta=419.07,440.5
XS Rating Curve= 0 ,0
Exp/Cntr(USF)=0,0
Exp/Cntr=0.3,0.1

Type RM Length L Ch R = 1 ,4466    ,332,332,332
XS GIS Cut Line= 3
2025452.60092466380680.4310322122025149.79064431381058.943882661
2024919.65483123381252.742462091
#Sta/Elev= 30
       0 2478.71    22.6 2468.13      53 2457.89    62.3 2452.12    81.5 2449.61
    97.3 2442.25   132.9 2428.87     179 2412.84     214 2401.81   224.3 2397.36
   241.1 2395.51   253.7 2390.06   278.9 2381.57   291.1 2379.06   316.7 2369.41
   333.5 2367.11   350.4 2365.25   354.6 2365.52   358.7 2367.18   374.5 2370.52
   398.4 2372.83   530.7 2372.87   540.8 2371.96   553.4 2372.55   639.2 2390.51
   660.6 2396.18   675.7 2398.31   710.7    2407   754.8 2419.32 785.599  2429.5
#Mann= 3 , 0 , 0
       0      .1       0   333.5    .045       0   358.7      .1       0
Bank Sta=333.5,358.7
XS Rating Curve= 0 ,0
Exp/Cntr(USF)=0,0
Exp/Cntr=0.3,0.1

Type RM Length L Ch R = 1 ,4135    ,315.9,315.9,315.9
XS GIS Cut Line= 3
2025436.09664247380520.6373797212025043.49099513380776.169503636
2024681.34613077381040.162956159
#Sta/Elev= 30
       0 2492.09    16.8 2489.26   62.652474.379   86.162466.526   106.8 2458.31
   118.5 2457.28     142    2448   196.8 2431.18     302 2403.24  313.172398.802
   329.9 2396.71  338.112393.459   380.8 2384.17     416  2374.1   452.4 2370.08
   491.5 2366.82  542.51 2367.75  563.352367.581     576 2366.41   586.5 2364.09
   597.7 2366.09   625.3 2378.29   699.2 2402.64   714.6 2406.01   759.2 2423.74
   771.4 2430.75   795.7  2432.3   813.2 2442.01  908.842469.282   916.6 2470.36
#Mann= 11 ,-1 , 0
       0      .1       0   62.65     .12       0   86.16      .1       0
  313.17      .1       0  338.11     .12       0   452.4      .1       0
  542.51      .1       0  563.35    .055       0     576    .045       0
   597.7    .055       0  908.84      .1       0
Bank Sta=576,597.7
XS Rating Curve= 0 ,0
Exp/Cntr(USF)=0,0
Exp/Cntr=0.3,0.1

Type RM Length L Ch R = 1 ,3819    ,169.9,169.9,169.9
XS GIS Cut Line= 2
2025307.25199009380368.5364434422024662.26609293380792.470835945
#Sta/Elev= 30
       0 2468.79    11.8 2464.97    23.6 2459.02    35.4 2457.46    62.4 2448.95
   113.9 2437.65   121.7 2434.56   217.7  2416.7   241.6 2411.52   255.2 2406.78
   274.9 2403.28   290.6 2402.87   302.3 2399.01   361.2 2388.22     373 2384.37
   396.6 2379.94   443.7 2366.42   486.9 2367.03   510.4 2365.63   541.8 2364.64
   546.3 2365.67   576.8 2367.28   596.8 2376.53   624.1 2385.61   654.9 2393.34
     691 2406.03   706.7 2413.41   730.3 2414.24   752.1 2425.03771.8336 2431.31
#Mann= 3 , 0 , 0
       0      .1       0   510.4    .045       0   546.3      .1       0
Bank Sta=510.4,546.3
XS Rating Curve= 0 ,0
Exp/Cntr(USF)=0,0
Exp/Cntr=0.3,0.1

Type RM Length L Ch R = 1 ,3649    ,145,145,145
XS GIS Cut Line= 2
 2025239.7938188380151.7234524782024537.50354446380710.171140506
#Sta/Elev= 30
       0 2509.59    39.7 2491.21    93.4 2472.98     103 2467.69   118.8 2464.66
   150.4 2451.94   213.7 2439.48  239.932432.185   253.4 2427.74   273.2  2424.5
   303.3 2416.32   341.4 2408.71   352.5 2403.83  398.672395.401   412.7 2393.02
   424.5 2386.53     509 2366.63   553.3 2364.73   569.7 2363.14   597.1 2364.93
   649.1 2372.82   710.3 2392.53   735.5  2401.6   749.5 2408.27   773.1 2409.35
   777.5 2411.12   786.8  2419.5   807.9 2422.53   819.2 2429.18   897.3 2457.27
#Mann= 5 ,-1 , 0
       0      .1       0  239.93      .1       0  398.67     .12       0
   553.3    .045       0   597.1    .055       0
Bank Sta=553.3,597.1
XS Rating Curve= 0 ,0
Exp/Cntr(USF)=0,0
Exp/Cntr=0.3,0.1

Type RM Length L Ch R = 1 ,3504    ,141,141,141
XS GIS Cut Line= 3
 2025147.7734678  380124.08508742024780.66892738380317.741152299
2024524.70612856380563.600156431
#Sta/Elev= 30
       0 2481.01   39.722466.412    83.4 2449.93   102.9 2447.02   112.8  2442.6
   127.6 2438.58   172.1  2429.9   186.9 2424.05   216.6 2415.88   236.4 2412.89
   287.4 2398.98   345.7  2385.1   368.7 2380.47   409.5 2375.93  495.282369.621
  520.582366.441   544.7 2364.65   548.3 2363.77   553.8  2364.6   599.4 2367.69
   613.7 2369.76   626.6 2373.05   643.5 2377.76   670.5 2387.88   710.8 2400.04
   732.1  2410.5   736.8 2411.81   746.3 2411.69   759.5 2413.59     770 2420.42
#Mann= 6 ,-1 , 0
       0      .1       0   39.72      .1       0  495.28     .12       0
  520.58    .055       0   544.7    .045       0   553.8    .055       0
Bank Sta=544.7,553.8
XS Rating Curve= 0 ,0
Exp/Cntr(USF)=0,0
Exp/Cntr=0.3,0.1

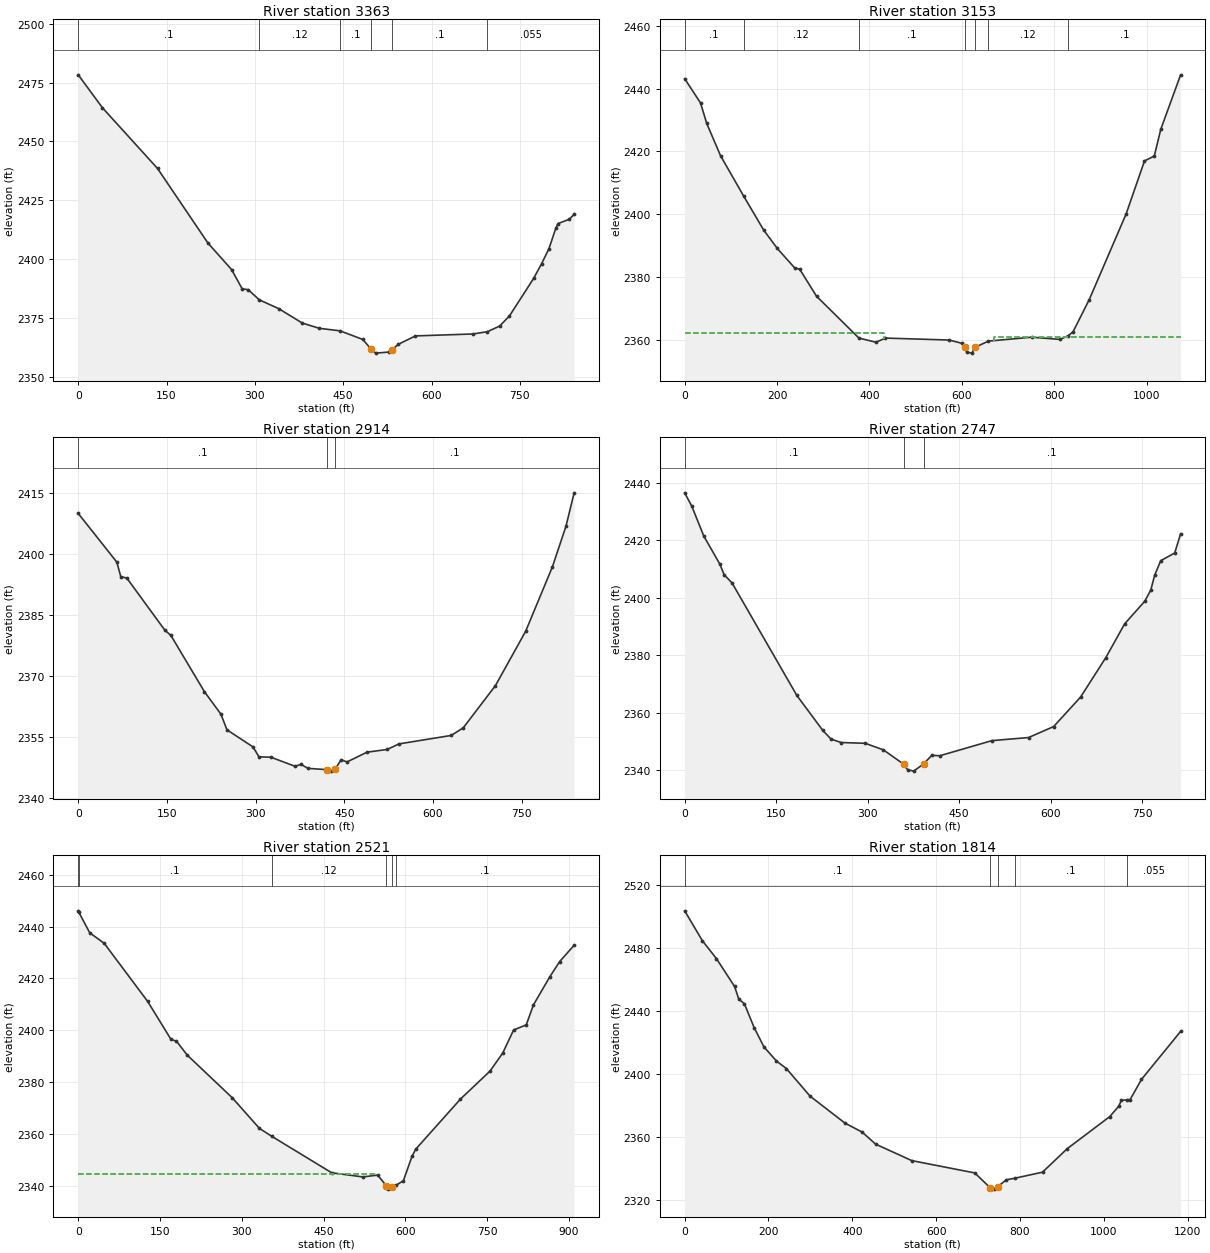
Type RM Length L Ch R = 1 ,3363    ,209.4,209.4,209.4
XS GIS Cut Line= 4
2025112.53043726380082.1645585582024700.74577841380247.630540196
2024555.96304448380328.483235769  2024429.983263380524.033941341
#Sta/Elev= 30
       0 2478.31    41.2 2464.29   134.7  2438.5   220.4 2406.76   260.4 2395.54
   278.4 2387.35   288.7 2386.96  307.512382.652   340.9 2378.86   380.7 2372.75
   409.6 2370.55  444.792369.464   483.4  2365.8   496.9 2361.82   505.1    2360
     527 2360.45   533.3 2361.54   543.7 2363.76   572.7 2367.32   670.3 2368.14
  695.022369.123   715.7 2371.51   732.3  2375.8   773.3 2391.73   786.9    2398
   799.5 2404.46   811.2  2413.2   815.1 2415.09   833.8  2416.9   842.2    2419
#Mann= 6 ,-1 , 0
       0      .1       0  307.51     .12       0  444.79      .1       0
   496.9    .045       0   533.3      .1       0  695.02    .055       0
Bank Sta=496.9,533.3
XS Rating Curve= 0 ,0
Exp/Cntr(USF)=0,0
Exp/Cntr=0.3,0.1

Type RM Length L Ch R = 1 ,3153    ,239.5,239.5,239.5
XS GIS Cut Line= 3
2025002.87661782379860.6537484152024639.03948774379935.113440152
2024224.43438602380502.022456786
#Sta/Elev= 30
       0  2443.2    34.3 2435.47    47.7 2428.94    77.8 2418.59  127.912405.713
   170.9 2394.97   200.5 2389.07   238.6 2382.79   248.8 2382.49   285.4 2373.84
  377.332360.478   414.3 2359.16   434.6 2360.49     573 2359.86   601.2 2358.78
   605.9 2357.51   610.6    2356   621.6 2355.69   628.9 2357.56  657.572359.518
   751.2 2360.77   812.6 2360.06  829.642361.183   840.7 2362.46   875.9 2372.77
   955.7 2400.06   995.5 2416.98  1016.7 2418.53  1030.8 2427.08  1073.7 2444.43
#Mann= 7 ,-1 , 0
       0      .1       0  127.91     .12       0  377.33      .1       0
   605.9    .045       0   628.9      .1       0  657.57     .12       0
  829.64      .1       0
#XS Ineff= 2 , 0
          430.61 2362.16  669.13         2360.81
Permanent Ineff=
       F       F
Bank Sta=605.9,628.9
XS Rating Curve= 0 ,0
Exp/Cntr(USF)=0,0
Exp/Cntr=0.3,0.1

Type RM Length L Ch R = 1 ,2914    ,166.9,166.9,166.9
XS GIS Cut Line= 3
2024407.90545742  379575.17350892024247.41600883380201.990789244
2024195.93826117380386.705060263
#Sta/Elev= 30
       0    2410    65.3 2398.03      72 2394.46    82.2 2394.11   146.5  2381.3
   156.8    2380   213.4 2366.19   241.4 2360.65   251.5 2356.82   295.6  2352.6
   305.7 2350.17     326 2350.07   366.7 2347.84   376.8 2348.31   388.7 2347.33
   420.6 2347.01   427.6 2346.65   434.5 2347.08   444.6 2349.45   454.7 2348.91
   488.5 2351.31   522.5 2351.97   542.4 2353.34   630.8 2355.42   651.2 2357.29
   705.7 2367.68   756.8 2381.04     802 2396.86   824.9 2406.82838.7902 2415.06
#Mann= 3 , 0 , 0
       0      .1       0   420.6    .045       0   434.5      .1       0
Bank Sta=420.6,434.5
XS Rating Curve= 0 ,0
Exp/Cntr(USF)=0,0
Exp/Cntr=0.3,0.1

Type RM Length L Ch R = 1 ,2747    ,226.3,226.3,226.3
XS GIS Cut Line= 3
2024096.01086865379584.2578173112024165.65723314380132.344424761
2024156.57292473 380392.76126587
#Sta/Elev= 30
       0 2436.46    11.6 2431.84    31.4 2421.41    57.9  2411.6    64.5 2408.07
    77.7 2405.14   183.9 2366.07   226.5  2353.9   239.8 2350.94   256.3 2349.72
     296 2349.45   325.8 2347.17   358.8 2342.23   365.5 2340.29   375.4 2339.78
   391.9 2342.33   405.1 2345.26   418.4 2345.13   503.8 2350.38   563.8 2351.45
   604.9 2355.26   649.2 2365.53   690.5 2379.23   721.4 2390.97   754.2 2398.76
   764.1 2402.64   770.6 2407.86   780.5 2412.89   803.4 2415.56   813.1 2422.24
#Mann= 3 , 0 , 0
       0      .1       0   358.8    .045       0   391.9      .1       0
Bank Sta=358.8,391.9
XS Rating Curve= 0 ,0
Exp/Cntr(USF)=0,0
Exp/Cntr=0.3,0.1

Type RM Length L Ch R = 1 ,2521    ,706.6,706.6,706.6
XS GIS Cut Line= 4
2023847.05913017379469.7403667962023909.67296186379938.497971595
2023945.21054201380107.724543724 2023984.1326536380368.333464804
#Sta/Elev= 30
       0 2446.05     .572445.732    21.2 2437.55    47.7 2433.51   127.4 2411.07
   170.2 2396.41   180.1 2395.77   199.9 2390.38   282.7 2373.86   332.3 2362.09
   354.92359.044   464.7 2344.97   521.6 2343.38   549.1 2344.06   565.2 2339.87
   568.6 2338.66   575.52339.482  582.672340.129   596.2  2341.9   612.1 2351.37
   618.8 2354.07   700.9 2373.42   755.1 2384.22   778.4 2391.19   798.3 2400.08
   821.5 2402.04   834.7 2409.78   864.6 2420.56   882.8 2426.49   909.3 2432.77
#Mann= 6 ,-1 , 0
       0      .1       0     .57      .1       0   354.9     .12       0
   565.2    .045       0   575.5     .12       0  582.67      .1       0
#XS Ineff= 2 , 0
          548.33 2344.45
Permanent Ineff=
       F       F
Bank Sta=565.2,575.5
XS Rating Curve= 0 ,0
Exp/Cntr(USF)=0,0
Exp/Cntr=0.3,0.1

Type RM Length L Ch R = 1 ,1814    ,263.2,263.2,263.2
XS GIS Cut Line= 4
2023400.30097975 379383.434815012023518.75958024380038.341649151
2023510.29825163380209.260487002 2023627.0645864380535.867771212
#Sta/Elev= 30
       0 2503.44    42.4 2484.43    75.7 2473.19   119.1 2455.48   129.1 2447.48
   142.4 2444.58   165.7 2429.47   189.1  2417.2   219.1 2408.21   242.7 2403.46
   299.1    2386   382.5 2368.88   423.4 2363.19   455.8 2355.53   541.9 2345.11
   692.1 2337.31   728.5 2328.06   738.1 2327.03   746.82328.604   767.7 2332.94
   788.42333.967   853.9 2337.78   912.9 2352.67  1014.4 2373.01  1035.3 2379.41
  1042.2 2383.22  1056.52383.665  1063.1 2383.81    1090 2396.56  1183.5    2427
#Mann= 5 ,-1 , 0
       0      .1       0   728.5    .045       0   746.8      .1       0
   788.4      .1       0  1056.5    .055       0
Bank Sta=728.5,746.8
XS Rating Curve= 0 ,0
Exp/Cntr(USF)=0,0
Exp/Cntr=0.3,0.1

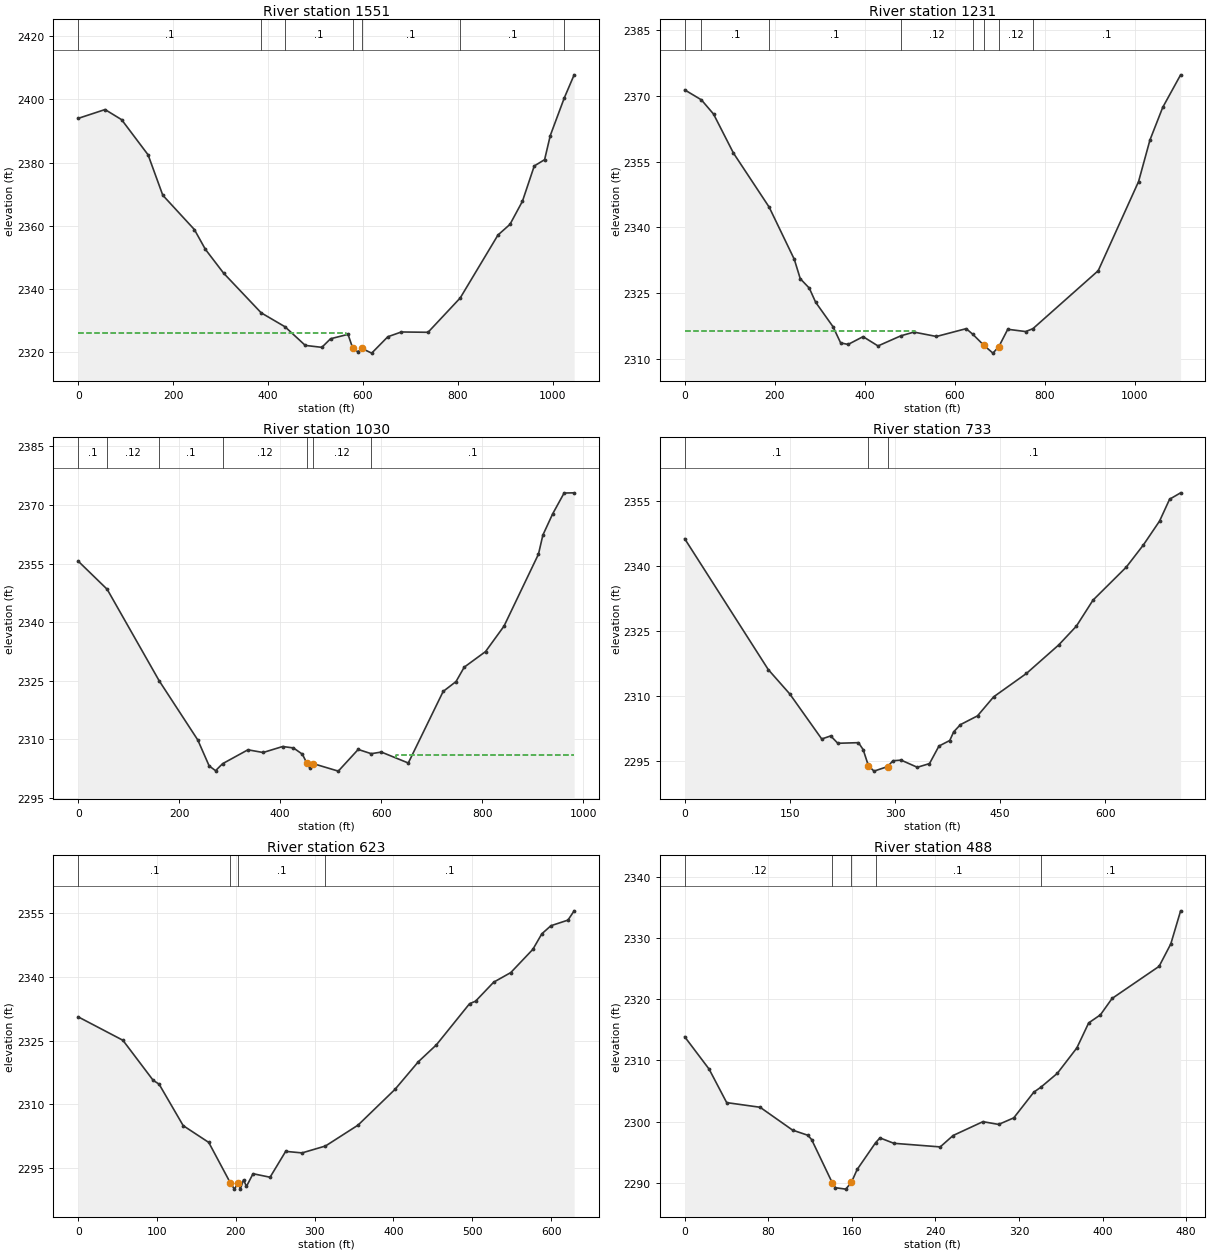
Type RM Length L Ch R = 1 ,1551    ,319.7,319.7,319.7
XS GIS Cut Line= 4
2023061.84783549379650.8127989742023241.22800195380146.646655314
2023320.76449085380243.1058014282023511.99051736380586.635742851
#Sta/Elev= 30
       0 2393.96    56.6 2396.75    91.5 2393.55   147.3 2382.43   178.3 2369.65
   244.9  2358.8     268 2352.57   306.4 2345.03  385.732332.463  435.982328.055
   478.7 2322.16   513.6 2321.55   531.9 2324.26   568.8 2325.66   578.7 2321.29
   589.7 2320.14     598 2321.19   618.7 2319.72   652.7  2324.9   681.2 2326.41
   737.5 2326.31  805.282337.161   884.9 2357.07   910.2 2360.44   936.5 2367.76
   961.4 2378.91   983.2  2380.9   995.2 2388.54 1024.912400.512  1045.5 2407.73
#Mann= 7 ,-1 , 0
       0      .1       0  385.73     .12       0  435.98      .1       0
   578.7    .045       0     598      .1       0  805.28      .1       0
 1024.91    .055       0
#XS Ineff= 2 , 0
          564.24 2325.97
Permanent Ineff=
       F       F
Bank Sta=578.7,598
XS Rating Curve= 0 ,0
Exp/Cntr(USF)=0,0
Exp/Cntr=0.3,0.1

Type RM Length L Ch R = 1 ,1231    ,201.7,201.7,201.7
XS GIS Cut Line= 4
2022976.51503793379758.7537762662023070.52980023380360.448254949
 2023085.5721622380505.2309888832023224.71401039380823.000885437
#Sta/Elev= 30
       0 2371.33   37.172369.047    64.1 2365.82   108.3 2356.94   187.62344.636
   243.5 2332.74   256.7 2328.33   276.7  2326.2   290.9 2322.97   329.5  2317.4
   346.4 2313.72     363 2313.37   396.2 2315.14   429.4 2313.03  480.142315.331
   509.1 2316.18   559.2 2315.18   625.2 2316.96  640.042315.673   664.82313.145
   684.6 2311.39   697.8 2312.88   717.6 2316.82   757.4  2316.3  773.49 2316.96
   918.5 2330.16  1008.1 2350.45  1033.4 2359.92  1061.8 2367.35  1101.5 2374.75
#Mann= 8 ,-1 , 0
       0      .1       0   37.17      .1       0   187.6      .1       0
  480.14     .12       0  640.04      .1       0   664.8    .045       0
   697.8     .12       0  773.49      .1       0
#XS Ineff= 2 , 0
          511.26 2316.34
Permanent Ineff=
       F       F
Bank Sta=664.8,697.8
XS Rating Curve= 0 ,0
Exp/Cntr(USF)=0,0
Exp/Cntr=0.3,0.1

Type RM Length L Ch R = 1 ,1030    ,296.6,296.6,296.6
XS GIS Cut Line= 4
2022640.47367089380046.8029777582022860.46821466380385.256122017
2022970.46548654380649.2495745392023153.23018444380877.705446914
#Sta/Elev= 30
       0 2355.62   57.332348.424   160.32325.003   236.8 2309.84   259.3 2303.21
     272 2301.97  285.942303.764   336.1 2307.32   366.2 2306.63   404.9 2308.16
   426.3  2307.8     444 2306.19  452.712303.908   458.2 2302.76  465.082303.792
   515.1 2301.86   554.5 2307.41  580.282306.329   600.4 2306.74   653.7 2303.94
   722.8 2322.27   748.3  2324.8   764.5 2328.48   806.7 2332.47   843.3 2338.99
   911.5 2357.41   920.3 2362.32   939.7 2367.75   962.3 2373.07   982.2 2373.12
#Mann= 7 ,-1 , 0
       0      .1       0   57.33     .12       0   160.3      .1       0
  285.94     .12       0  452.71    .045       0  465.08     .12       0
  580.28      .1       0
#XS Ineff= 2 , 0
          401.77 2307.52   630.3         2305.93
Permanent Ineff=
       F       F
Bank Sta=452.71,465.08
XS Rating Curve= 0 ,0
Exp/Cntr(USF)=0,0
Exp/Cntr=0.3,0.1

Type RM Length L Ch R = 1 ,733     ,109.9,109.9,109.9
XS GIS Cut Line= 3
2022475.97586873380510.8572752112022842.37630797 380737.96498548
  2023042.231093380928.735462107
#Sta/Elev= 30
       0 2346.23   119.2 2316.02   149.9 2310.39   195.5 2299.99   208.3  2300.7
   218.4    2299   247.9 2299.14   254.6 2297.53   262.1  2293.8   270.1 2292.57
   289.4 2293.62   297.1 2294.96   308.7 2295.11   331.8 2293.46   349.2 2294.31
   362.7 2298.36   378.1 2299.64   383.7 2301.64   393.3  2303.3   417.7 2305.33
   440.7 2309.72   487.4 2315.11   533.5  2321.7   558.7 2326.04   582.4 2332.04
   629.9 2339.67   654.2 2344.77   677.4 2350.31   691.7 2355.35   707.4 2356.82
#Mann= 3 , 0 , 0
       0      .1       0   262.1    .045       0   289.4      .1       0
Bank Sta=262.1,289.4
XS Rating Curve= 0 ,0
Exp/Cntr(USF)=0,0
Exp/Cntr=0.3,0.1

Type RM Length L Ch R = 1 ,623     ,134.6,134.6,134.6
XS GIS Cut Line= 2
2022479.70842736380645.8650430972023019.54119246380969.087795864
#Sta/Elev= 30
       0 2330.62    56.7 2325.11    95.1 2315.68   102.6 2314.78   133.2 2305.01
   165.6 2301.06   193.1  2291.5   198.2 2290.06   202.7 2291.46   205.8 2290.17
   209.7 2292.24   213.5 2290.71   221.8 2293.69   243.4 2292.86   263.2 2298.95
     284 2298.59  313.712300.215     355 2305.13   401.9 2313.55   431.5 2320.05
   454.4 2324.03   496.5 2333.72   504.1 2334.31   527.1 2338.79   548.8 2341.05
   576.8 2346.52   588.2 2350.18   599.7 2352.08   621.3  2353.4   629.2 2355.59
#Mann= 4 ,-1 , 0
       0      .1       0   193.1    .045       0   202.7      .1       0
  313.71      .1       0
Bank Sta=193.1,202.7
XS Rating Curve= 0 ,0
Exp/Cntr(USF)=0,0
Exp/Cntr=0.3,0.1

Type RM Length L Ch R = 1 ,488     ,244.4,244.4,244.4
XS GIS Cut Line= 3
2022467.86256732380810.0148180622022709.85656546380925.088887111
2022890.92899764381024.932564667
#Sta/Elev= 30
       0 2313.85    23.4 2308.56    40.2  2303.1    72.2 2302.34   103.3 2298.61
   117.9 2297.77   121.5 2297.07  141.322289.999   144.3 2289.21   154.2 2288.98
   159.6 2290.09   165.1 2292.19  182.712296.545   186.9 2297.34   200.2 2296.46
   244.6 2295.87   256.9 2297.73   285.5 2299.99   300.5 2299.54     315 2300.61
   334.2 2304.81  340.912305.609   356.7 2307.88   375.4 2312.03   386.7 2316.11
   397.9 2317.42   409.1  2320.1   454.1 2325.34   465.3    2329   474.7  2334.4
#Mann= 5 ,-1 , 0
       0     .12       0  141.32    .045       0   159.6     .12       0
  182.71      .1       0  340.91      .1       0
Bank Sta=141.32,159.6
XS Rating Curve= 0 ,0
Exp/Cntr(USF)=0,0
Exp/Cntr=0.3,0.1

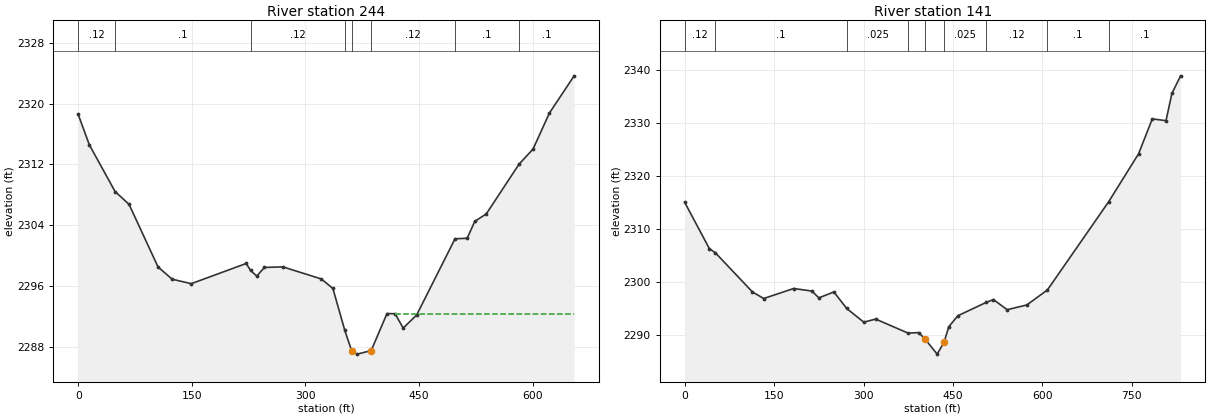
Type RM Length L Ch R = 1 ,244     ,103.2,103.2,103.2
XS GIS Cut Line= 4
2022322.32771528380850.6291953742022516.93827323381077.392802027
2022647.24273377 381133.237570832022857.08368321381175.544213862
#Sta/Elev= 30
       0 2318.57    14.7 2314.57   48.642308.421    67.1 2306.73   105.4 2298.48
     124 2296.87   149.2 2296.28   221.8 2298.94  227.542298.017   235.8 2297.28
   245.8 2298.42   270.3 2298.49     321  2296.9   336.2 2295.65  351.922290.132
   361.2 2287.37   368.4    2287   386.8 2287.47   407.6 2292.34   418.3 2292.32
     429 2290.43   446.8 2292.16  497.462302.195   513.5 2302.26   523.5 2304.49
   538.7 2305.47  581.832312.006   600.5 2314.02     622 2318.75   654.7 2323.66
#Mann= 8 ,-1 , 0
       0     .12       0   48.64      .1       0  227.54     .12       0
  351.92      .1       0   361.2    .045       0   386.8     .12       0
  497.46      .1       0  581.83      .1       0
#XS Ineff= 2 , 0
                          418.26         2292.34
Permanent Ineff=
       F       F
Bank Sta=361.2,386.8
XS Rating Curve= 0 ,0
Exp/Cntr(USF)=0,0
Exp/Cntr=0.3,0.1

Type RM Length L Ch R = 1 ,141     ,140,141,140
XS GIS Cut Line= 4
 2022287.8360505380870.9411955252022498.68527748381169.644267086
2022618.16650611 381243.441496532022943.22573104381268.040573012
#Sta/Elev= 30
       0    2315    41.4 2306.25   51.512305.466   113.7 2298.08   132.6 2296.84
   182.8 2298.73   213.4 2298.25   225.1 2296.96   250.3 2298.08  271.812294.967
   300.5 2292.38   320.4 2292.96  374.94 2290.31   392.8 2290.41   403.7 2289.12
   423.6 2286.35   435.3 2288.63   442.9 2291.49   458.3 2293.59  506.322296.135
     518 2296.64     541 2294.73   573.9 2295.62  608.492298.451  711.372315.111
   761.5 2324.15   784.5 2330.73   807.5 2330.39   817.4 2335.54     832 2338.85
#Mann= 9 ,-1 , 0
       0     .12       0   51.51      .1       0  271.81    .025       0
  374.94      .1       0   403.7    .045       0   435.3    .025       0
  506.32     .12       0  608.49      .1       0  711.37      .1       0
Bank Sta=403.7,435.3
XS Rating Curve= 0 ,0
Exp/Cntr(USF)=0,0
Exp/Cntr=0.3,0.1
LCMann Table=0

Chan Stop Cuts=-1
Use User Specified Reach Order=0
Composite Channel Slope=5